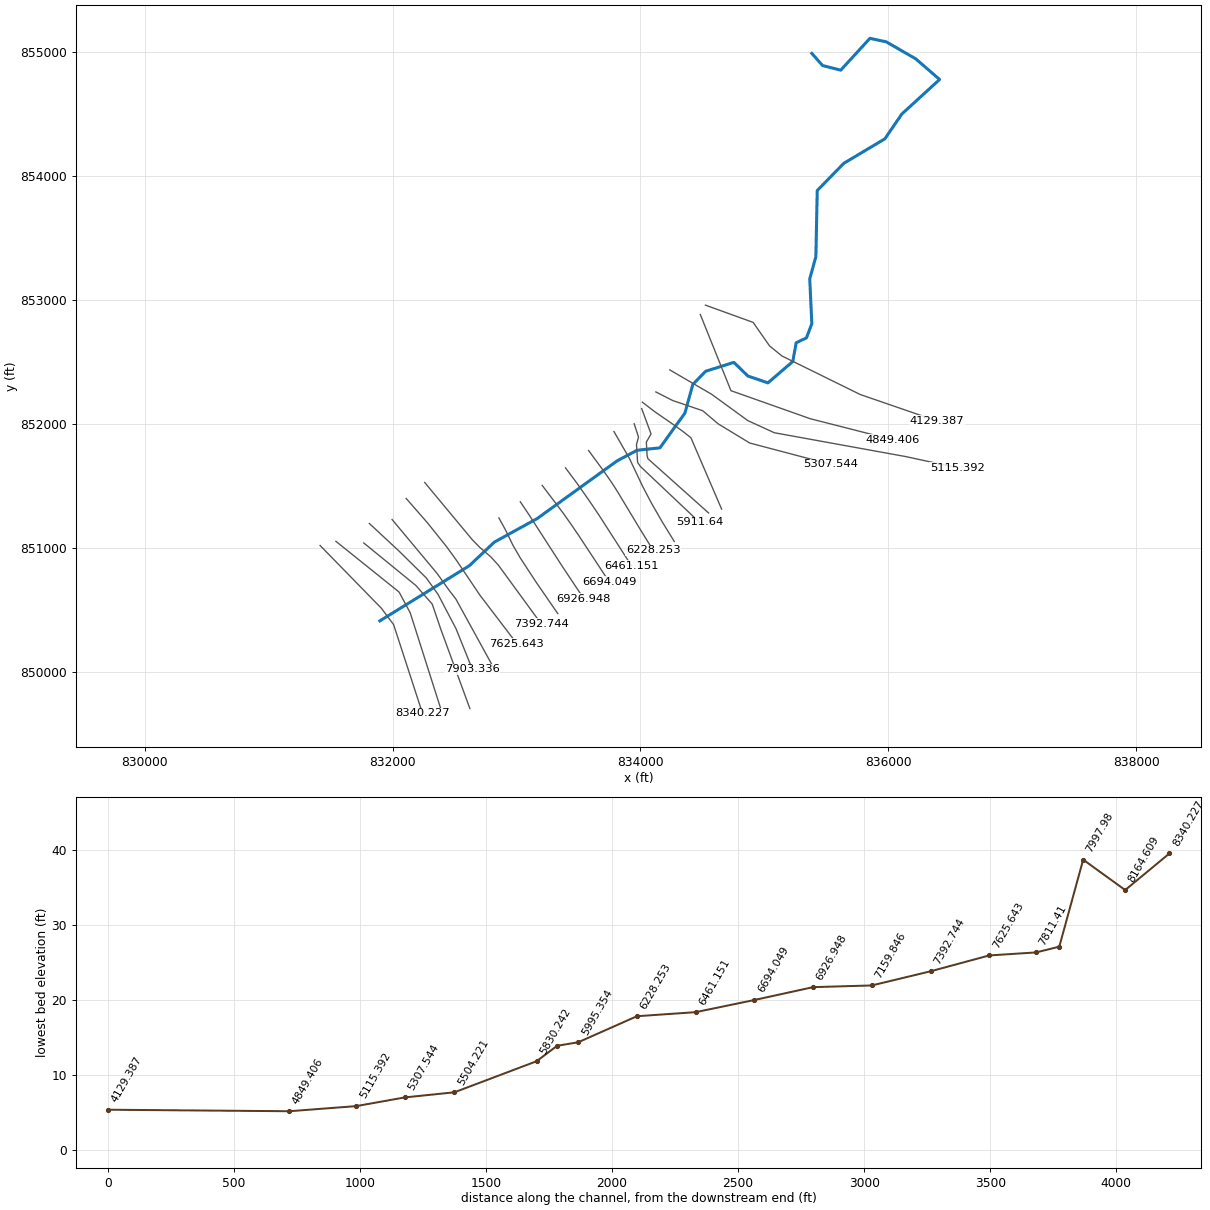
--- 18501_ras.prj (project) ---

Proj Title=18501
Current Plan=p01
Default Exp/Contr=0.3,0.1
English Units
Geom File=g01
Flow File=f01
Plan File=p01
Y Axis Title=Elevation
X Axis Title(PF)=Main Channel Distance
X Axis Title(XS)=Station
BEGIN DESCRIPTION:
RFD model 18501 exported to HEC-RAS
END DESCRIPTION:

--- 18501_ras.p01 (plan) ---

Plan Title=Plan 01
Program Version=4.10
Short Identifier=Plan 01
Geom File=g01
Flow File=f01
Subcritical Flow
Calc Critical at every XS
Secant Critical Depth

--- 18501_ras.f01 (steady flow) ---

Flow Title=Flow 01
Program Version=5.01
Number of Profiles= 6
Profile Names=10yr,25yr,50yr,100yr,100plus,500yr
River Rch & RM=18501,20,8340.227
   256.1  400.34  532.48  649.26  947.92 1515.54
River Rch & RM=18501,20,8164.609
  753.96 1183.81  1580.6 1930.72 2818.86 3874.55
River Rch & RM=18501,20, 7997.98
  756.06 1187.22 1585.25  1936.5 2827.29 3884.93
River Rch & RM=18501,20,7903.336
  951.74 1498.86 2005.58 2453.81 3582.56 4776.28
River Rch & RM=18501,20, 7811.41
   956.6 1506.73 2016.33 2467.16 3602.06  4799.5
River Rch & RM=18501,20,7625.643
 1000.34 1578.06 2113.98 2588.95 3779.87 5011.94
River Rch & RM=18501,20,7392.744
 1005.07 1585.75 2124.52 2602.08 3799.04 5034.73
River Rch & RM=18501,20,7159.846
  1013.5 1599.44 2143.21 2625.33 3832.99 5074.85
River Rch & RM=18501,20,6926.948
 1017.35 1605.73 2151.82 2636.09 3848.69 5093.53
River Rch & RM=18501,20,6694.049
 1027.33 1621.97 2174.04 2663.78 3889.12 5141.44
River Rch & RM=18501,20,6461.151
 1031.17 1628.24 2182.64  2674.5 3904.78 5160.02
River Rch & RM=18501,20,6228.253
 1036.92 1637.64 2195.51 2690.57 3928.23 5187.85
River Rch & RM=18501,20,5995.354
 1091.67 1726.62 2317.12 2841.98 4149.28 5447.41
River Rch & RM=18501,20, 5911.64
 1094.92 1731.93 2324.39 2851.04 4162.53 5462.99
River Rch & RM=18501,20,5830.242
 1096.28 1734.14 2327.42 2854.82 4168.04 5469.47
River Rch & RM=18501,20,5504.221
 1100.06 1740.32 2335.89 2865.39 4183.47 5487.61
River Rch & RM=18501,20,5307.544
  1102.5 1744.29 2341.33 2872.18 4193.39 5499.26
Boundary for River Rch & Prof#=18501,20,1
Up Type= 0
Dn Type= 2
Boundary for River Rch & Prof#=18501,20,2
Up Type= 0
Dn Type= 2
Boundary for River Rch & Prof#=18501,20,2
Up Type= 0
Dn Type= 2
Boundary for River Rch & Prof#=18501,20,2
Up Type= 0
Dn Type= 2
Boundary for River Rch & Prof#=18501,20,2
Up Type= 0
Dn Type= 2
Boundary for River Rch & Prof#=18501,20,2
Up Type= 0
Dn Type= 2

--- 18501_ras.g01 (geometry) ---

Geom Title=18501
Program Version=4.10

River Reach=18501,20
Reach XY= 30
831896.437561363850410.463210493832618.047000799850855.300860097
832820.580045759851046.205992824833165.899531871851236.043796513
833810.989231053851701.862112469833972.335543514851787.608811802
834156.704324516 851806.96675123834358.370190473852087.292118593
 834422.27862552852318.482970789834525.467369291852425.033027241
834753.817074002852496.942703268834866.484730722852387.075848417
835028.622690025 852331.66398581835229.518743278852504.410706643
835256.862493305852655.452373291835339.583552479852694.838562775
835382.979169189852808.581297075835366.092186603853170.631373102
835415.625373067853350.791521382835426.698292108853884.064699662
835641.115237833854103.724714987835972.438615799854301.261081426
836109.485443414854501.508246787 836414.41457659 854780.45237329
836221.285606147854947.268083224835984.727076593855083.837789963
835851.914576619855112.483623315835616.286341608854855.535891303
835469.161116901 854893.05712246835382.896394462854991.239598027

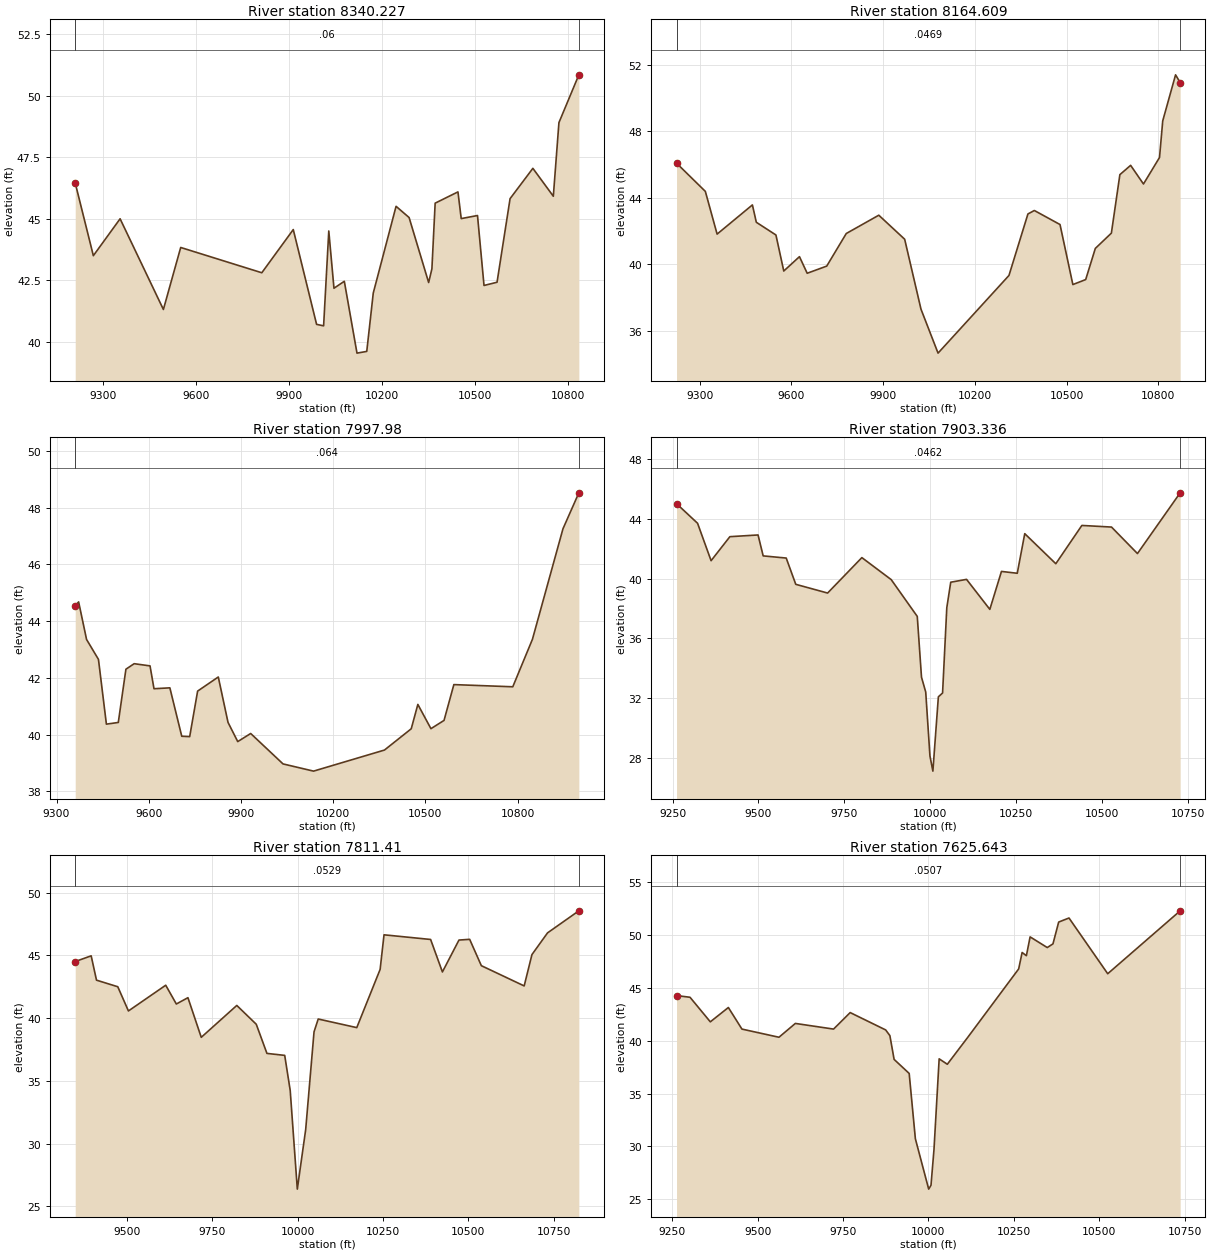
Type RM Length L Ch R = 1 ,8340.227,175.618500,175.618500,175.618500
XS GIS Cut Line= 4
831414.109191656851018.662056416831908.600168705850512.325046703
832007.421353072850380.056692228832240.511159956849663.812570885
#Sta/Elev= 30
9209.63546.45872 9268.1643.50327 9354.5345.003429494.30741.317899550.21843.83743
9812.03642.809959913.63744.564889988.93440.7127710011.6140.6523210028.32 44.5081
10045.0242.1806410078.4442.4632210119.3539.54352 10150.939.6134810171.9341.98685
10245.5545.5102610287.61  45.05410350.7142.4129910361.2242.9681510371.7445.63841
10445.3546.0960310455.8745.0112110508.4545.1364410529.4842.2931310571.5542.42433
10613.6145.8213210687.2347.0536210753.2645.9198910771.3648.91138 10835.750.85424
#Mann= 3 , 0 , 0
9209.635    0.06       09209.635    0.06       0 10835.7    0.06       0
#XS Ineff= 2 , 0
       09936.025        10056.94       0
Bank Sta=9209.635,10835.7
Exp/Cntr=0.3,0.1

Type RM Length L Ch R = 1 ,8164.609,166.628100,166.628100,166.628100
XS GIS Cut Line= 4
831541.536252528851052.392749012832051.510804564850643.073075294
832141.210033476850475.837224767832384.803567141849710.660755023
#Sta/Elev= 30
9224.36246.093849318.56244.39631 9357.0341.825759472.43443.582429485.25742.53815
 9549.3741.772739575.01539.605819626.30640.469889651.54539.470659715.44839.90205
9779.35241.861849885.66842.962719970.29441.5175810023.6237.3121910079.4334.66691
10311.3139.3389610373.2843.0369610394.2743.2461110478.2242.40171 10520.2 38.7909
10562.1839.0915810593.6640.9649810646.1441.8843110673.9345.40266 10709.145.96232
10751.0844.8395210803.5546.4353210814.0548.6374910856.0351.4072110871.0750.94149
#Mann= 3 , 0 , 0
9224.362  0.0469       09224.362  0.0469       010871.07  0.0469       0
#XS Ineff= 2 , 0
       09940.216        10065.28       0
Bank Sta=9224.362,10871.07
Exp/Cntr=0.3,0.1

Type RM Length L Ch R = 1 , 7997.98,94.644800,94.644800,94.644800
XS GIS Cut Line= 5
831766.407536417851039.275257438832186.819810927850696.284482256
832319.088165402850545.772216797832389.023157418850340.528218448
832622.792342633849703.165045574
#Sta/Elev= 30
9360.82444.536569371.91444.673879397.72543.350219436.44342.647949462.25440.36617
9500.972 40.42559525.77742.301929552.59542.496489604.21842.418959617.12441.61421
9668.74741.645659707.46539.939339733.27639.926569759.08841.530899826.33842.02762
9857.97640.428169889.61439.751269931.73640.0367110036.9838.9648410136.2838.71079
   1036739.4532510454.1240.2029210475.6141.0612310518.22 40.206510560.8240.49796
10592.7841.75961 10784.541.6826110848.4143.3548610947.8247.2509310999.4948.51737
#Mann= 3 , 0 , 0
9360.824   0.064       09360.824   0.064       010999.49   0.064       0
#XS Ineff= 2 , 0
       09942.975        10075.51       0
Bank Sta=9360.824,10999.49
Exp/Cntr=0.3,0.1

Type RM Length L Ch R = 1 ,7903.336,91.926000,91.926000,91.926000
XS GIS Cut Line= 6
831811.381793171851196.685156167832053.118423402850971.813872278
832272.527966201850755.263855413832365.755235672850624.577823296
 832510.64923054850348.129848018832642.917585015850019.739450678
#Sta/Elev= 30
9261.62845.015869322.83143.704879362.17441.201819416.80542.808229498.75142.92322
9513.69741.523449580.69741.379059608.47939.622379701.13639.038919800.78741.40866
9886.20239.935019961.94537.476429974.25633.413359986.56832.41624 9998.8228.14677
10007.36 27.130710023.3232.0992810035.5732.3552310047.8338.0536810059.2939.76299
10105.2839.9532710173.0237.9482810206.8940.4848610252.8440.3609610274.6343.00893
10364.9640.9999910440.7743.5597110527.02 43.451610602.4841.6797710726.7445.74076
#Mann= 3 , 0 , 0
9261.628  0.0462       09261.628  0.0462       010726.74  0.0462       0
#XS Ineff= 2 , 0
       09946.323        10074.52       0
Bank Sta=9261.628,10726.74
Exp/Cntr=0.3,0.1

Type RM Length L Ch R = 1 , 7811.41,185.767000,185.767000,185.767000
XS GIS Cut Line= 6
831995.026675075851228.541921407832357.409958482850794.262763351
832408.006865203850723.809342876832450.637227952850663.576731205
832510.097014517850586.320595846832824.147893667850014.516457766
#Sta/Elev= 30
9348.20644.518249394.95444.972269410.55143.033059472.93842.506899504.13140.57588
9613.43642.627759644.54941.129699678.52841.634519717.58338.471859821.73141.01528
 9878.8239.513539910.05637.189789962.15937.031599978.26234.235249999.09426.36265
 10023.631.1112510048.1138.9114710060.3639.9325210173.3539.24639 10241.843.89156
10253.2146.6496510389.7546.2786110424.3543.6874110472.8446.2313810504.2146.28883
10538.4344.1875710663.93 42.572410686.7545.0727510732.3946.8029710824.2148.56327
#Mann= 3 , 0 , 0
9348.206  0.0529       09348.206  0.0529       010824.21  0.0529       0
#XS Ineff= 2 , 0
       09884.069        10075.97       0
Bank Sta=9348.206,10824.21
Exp/Cntr=0.3,0.1

Type RM Length L Ch R = 1 ,7625.643,232.898400,232.898400,232.898400
XS GIS Cut Line= 6
832108.643123095851398.691834148832279.857257482851202.656130142
832436.871488877851006.695447416832512.674800692850902.005474565
832705.678725089850615.597563844833001.823718295850227.267991885
#Sta/Elev= 30
9262.77844.289749302.29744.126149361.67741.800619414.51543.157769454.227 41.1143
9562.65440.34167 9610.6641.649929722.50841.114649771.15642.677629875.05441.03442
  9887.440.494929899.74638.244829943.89236.91496 9962.01   30.73   1000125.96221
10007.7526.3279410016.51 29.714210031.6538.2965710055.5537.7849110115.3140.33022
10264.4446.8120910274.5448.3680810287.0148.0609410297.9149.84477 10348.148.83448
10364.83 49.182210381.5651.2474610411.7451.6320810525.1546.3557710737.23 52.3114
#Mann= 3 , 0 , 0
9262.778  0.0507       09262.778  0.0507       010737.23  0.0507       0
#XS Ineff= 2 , 0
       0 9872.14        10116.62       0
Bank Sta=9262.778,10737.23
Exp/Cntr=0.3,0.1

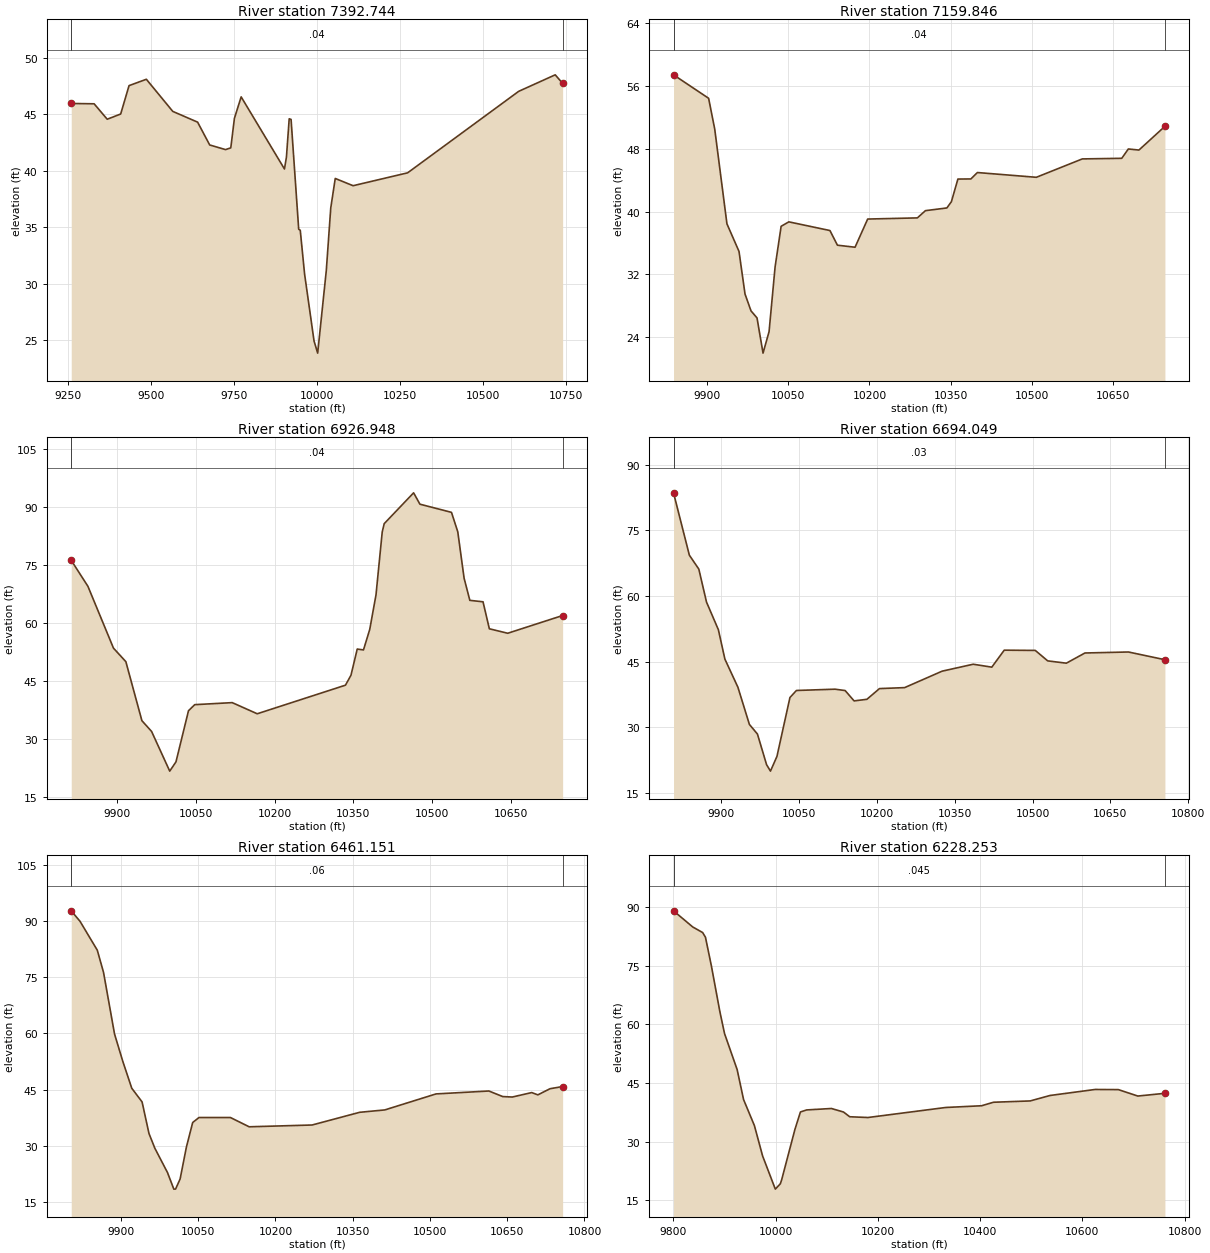
Type RM Length L Ch R = 1 ,7392.744,232.898300,232.898300,232.898300
XS GIS Cut Line= 6
832258.287530967851527.497170989832641.470509749851066.560619414
832701.425978526851004.997033518832793.145468416850925.822305057
832852.726176155850860.263599364833198.025116388850387.529487487
#Sta/Elev= 30
9259.65745.967959328.67145.93943 9368.1144.572539408.64445.035659433.84247.54853
9486.04148.112449565.66545.266749640.45744.31391 9676.8942.292929724.55841.88117
9740.44742.036979751.35544.649299771.68946.553599902.19540.16301 9908.13 41.2252
9916.44544.615289922.10944.552829945.06734.825939949.76734.736169962.90630.83685
9991.31624.9274310002.26 23.850610028.2231.1646210041.6436.7065510055.2139.32537
10108.9638.6828810273.3339.8243210607.9847.0440710718.0548.5065910740.3647.74883
#Mann= 3 , 0 , 0
9259.657    0.04       09259.657    0.04       010740.36    0.04       0
#XS Ineff= 2 , 0
       09888.094         10149.1       0
Bank Sta=9259.657,10740.36
Exp/Cntr=0.3,0.1

Type RM Length L Ch R = 1 ,7159.846,232.898400,232.898400,232.898400
XS GIS Cut Line= 6
832857.051311177851241.309452007832908.720302759851147.575606142
832971.247370558851019.242408304833030.429971423850917.290294064
833157.493827536850722.962010394833332.234316701850469.335416636
#Sta/Elev= 30
9838.00557.454329902.83354.463949914.11650.542599936.68338.459169959.00434.93442
9970.09229.50222 9981.1827.355649992.26826.4553410003.3921.9664310014.53 24.7079
10025.6832.9722210036.8238.1390910051.0138.7054810126.9937.5984510140.8235.72985
10173.3935.4692210196.7239.0639610288.5539.2107410303.3840.1325410343.08 40.4799
10351.41 41.280410363.4244.1632810387.4344.1774210399.4444.99422 10508.344.38793
 10593.346.7316810666.1746.8088410678.31 47.9985 10697.947.8613310745.9150.88467
#Mann= 3 , 0 , 0
9838.005    0.04       09838.005    0.04       010745.91    0.04       0
#XS Ineff= 2 , 0
       0                10151.91       0
Bank Sta=9838.005,10745.91
Exp/Cntr=0.3,0.1

Type RM Length L Ch R = 1 ,6926.948,232.898300,232.898300,232.898300
XS GIS Cut Line= 6
833030.175688305851371.365942208833100.776668387851266.111913475
833132.902155107 851216.22666659833133.976058095851214.539440354
833371.158908668850846.778518713833542.926443828850588.867831541
#Sta/Elev= 30
9812.92676.199589844.67469.492469893.39253.504489916.92250.022899947.46634.77607
9965.93531.9910310000.4521.7408610012.3524.1378110036.15 37.332510048.0538.91186
10119.4539.4356510167.0436.55715   1033543.9436710345.5346.5125710357.4353.27554
10369.3353.0521310381.2358.3324410393.1367.2381310405.0383.52996 10408.885.67467
10464.7893.6366710476.7990.7012610536.8788.5935510548.8883.56652 10560.9 71.5815
10571.8265.8627710596.9465.4826510608.9658.5139310643.9857.3586510748.49 61.9445
#Mann= 3 , 0 , 0
9812.926    0.04       09812.926    0.04       010748.49    0.04       0
#XS Ineff= 2 , 0
       0                10141.36       0
Bank Sta=9812.926,10748.49
Exp/Cntr=0.3,0.1

Type RM Length L Ch R = 1 ,6694.049,232.898400,232.898400,232.898400
XS GIS Cut Line= 6
833206.541596707851503.857572898833323.460477721851349.888366181
833375.582833114 851280.39228113833433.030476074851199.758149832
833496.165459655851107.345837247833747.019007995850726.211658399
#Sta/Elev= 30
 9807.6783.594089838.19369.35484 9856.4666.171229871.26658.638779894.12852.33428
9906.68445.625069931.79639.194919953.94730.695329969.46428.50025 9987.0221.51948
9994.57620.0288610007.11 23.409810032.1136.8382310044.6138.4483110119.0538.74515
10138.5738.43109 10155.836.0690710180.4436.4330210204.75 38.880910253.1939.10228
10325.5542.8609210385.4144.4441310421.3243.7776310445.26 47.654910505.1247.59909
10529.0645.2099310564.9844.6834210600.89 47.0128 10684.747.2384810755.0745.47625
#Mann= 3 , 0 , 0
 9807.67    0.03       0 9807.67    0.03       010755.07    0.03       0
#XS Ineff= 2 , 0
       0                10149.25       0
Bank Sta=9807.67,10755.07
Exp/Cntr=0.3,0.1

Type RM Length L Ch R = 1 ,6461.151,232.898300,232.898300,232.898300
XS GIS Cut Line= 6
833394.767575491851645.258862373833484.916287953851524.379579104
833510.849151738851488.119837203833584.969152594851382.308816996
833665.747907735851262.667994801833927.838840329850854.491639199
#Sta/Elev= 30
9803.62892.701429820.74489.890739854.19882.204749866.32476.269529887.65259.85258
9903.74852.513739921.10745.348939941.17241.691659954.56533.261149965.95329.33215
9990.54122.8219110002.8218.4110110006.2218.4237910015.02 21.123910027.2329.65454
10039.4436.1963610051.6537.5249610112.6937.5248910149.0735.0497910271.2135.52676
 10363.738.9213610412.3839.5529110511.7743.8242510614.4144.6056610641.3243.12061
10659.8342.99439 10697.644.1876410709.4843.5735410733.2545.2187110757.6245.79205
#Mann= 3 , 0 , 0
9803.628    0.06       09803.628    0.06       010757.62    0.06       0
#XS Ineff= 2 , 0
       0                 10155.6       0
Bank Sta=9803.628,10757.62
Exp/Cntr=0.3,0.1

Type RM Length L Ch R = 1 ,6228.253,232.898400,232.898400,232.898400
XS GIS Cut Line= 6
833581.197757569851785.311092745 833700.17412769 851623.74550707
833766.225810103851528.855540242833814.140876989851454.080063021
833993.873689493 851155.48496979834102.833368077850978.912166415
#Sta/Elev= 30
9800.35489.058879837.99884.924249857.35783.497199862.83682.294229874.22175.08974
9891.08563.215549900.09357.678189924.81248.436449937.35140.786759958.53934.12215
9974.60826.341949999.445 17.868910009.2519.2372810011.7820.2295510037.8433.17103
10048.5937.60764 10060.738.1266810109.1838.4946110132.8937.5880210144.9636.37997
10180.5936.1875610332.7538.7549410402.7839.1931910426.1240.0930310497.9640.42934
10536.7441.8239110625.0243.3622410670.3543.3243510708.4341.6776310761.4342.38034
#Mann= 3 , 0 , 0
9800.354   0.045       09800.354   0.045       010761.43   0.045       0
#XS Ineff= 2 , 0
       0                 10162.8       0
Bank Sta=9800.354,10761.43
Exp/Cntr=0.3,0.1

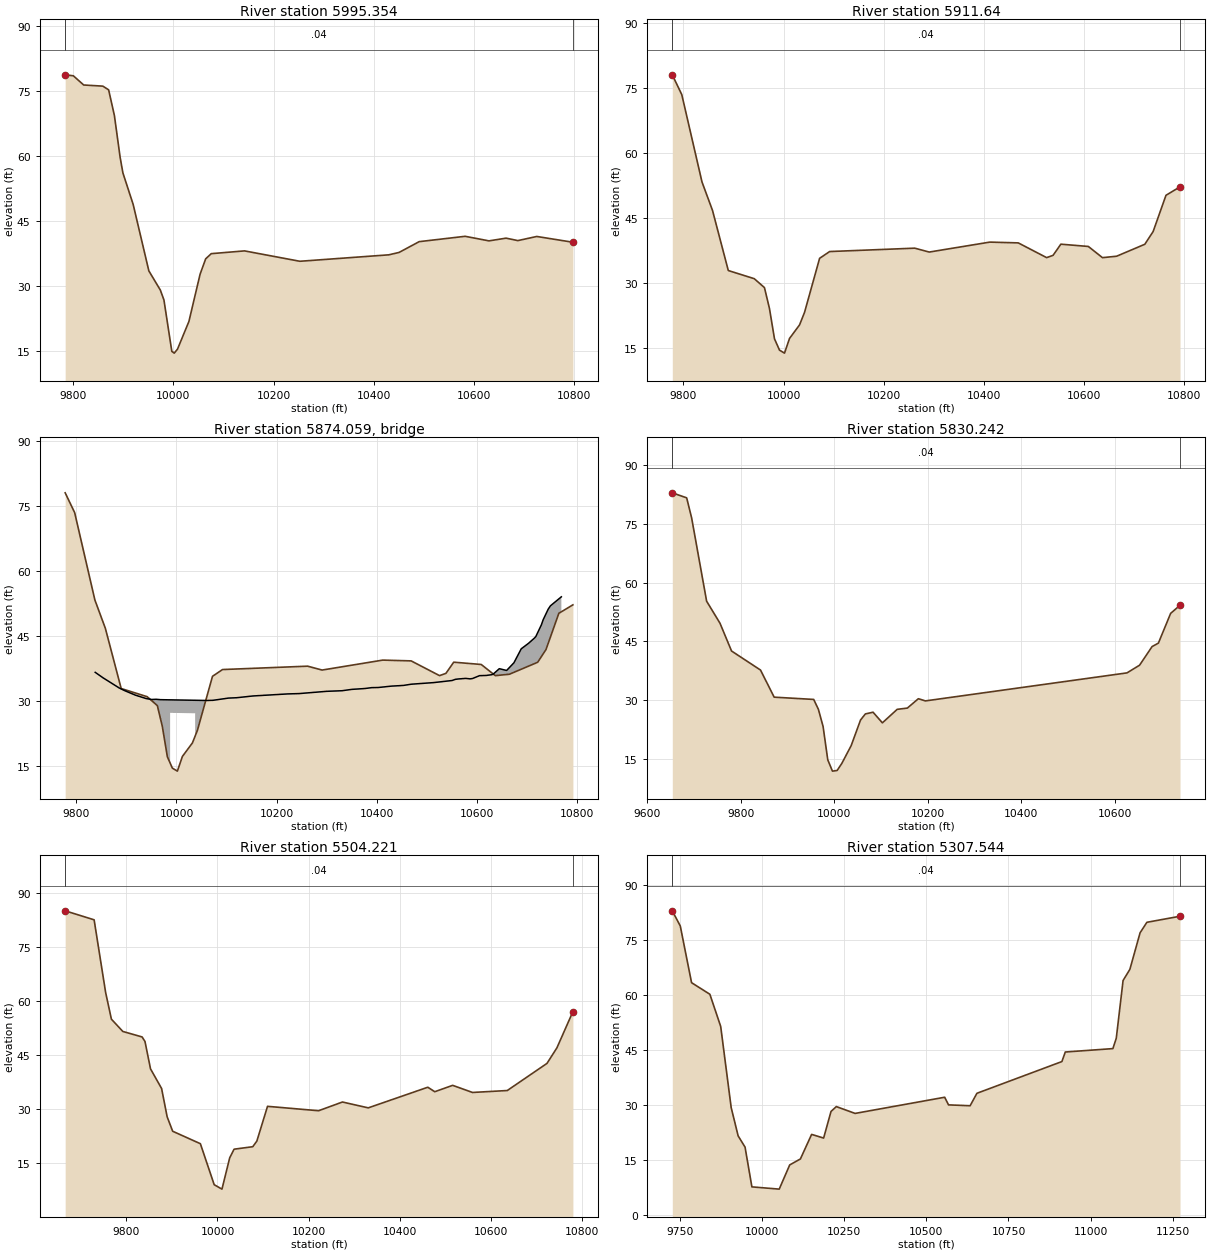
Type RM Length L Ch R = 1 ,5995.354,83.714500,83.714500,83.714500
XS GIS Cut Line= 6
833785.648783556851938.901149207833909.091625599851724.472478371
834018.292966686851494.381286633834088.348035651851360.872135858
834174.318979958851211.461522378834272.749795731851051.411861993
#Sta/Elev= 30
9783.96678.723429800.28278.500669820.927 76.37179859.12876.109819870.70575.24985
 9882.1969.32441 9893.6559.643629899.16756.054729919.64348.777189950.94733.41674
9973.86628.982259981.07326.683469996.785 14.817210001.6314.4045810008.1515.33023
10030.8521.7069310053.1932.6385810064.3636.1991210075.5337.3926410141.9238.03201
10252.3435.6323910429.7237.1215310450.26 37.673110490.3640.1660610582.1441.40363
10629.6940.3482110663.8540.9774110687.3340.4123110725.1441.36564 10797.240.02813
#Mann= 3 , 0 , 0
9783.966    0.04       09783.966    0.04       0 10797.2    0.04       0
#XS Ineff= 2 , 0
       0                 10171.4       0
Bank Sta=9783.966,10797.2
Exp/Cntr=0.3,0.1

Type RM Length L Ch R = 1 , 5911.64,81.397800,81.397800,81.397800
XS GIS Cut Line= 6
833949.150423944 852001.45415616833983.999199837851893.962861404
833967.801881433851834.572693974833976.636782378851689.778484136
833998.724034697851657.383847371834474.910311013851207.113989264
#Sta/Elev= 30
9777.65378.059899796.62173.49877    983753.370449858.02546.809789889.56232.96368
9941.40431.087459961.79829.031979971.81124.206749981.82517.238569991.83914.62404
10001.8513.9328510011.8717.3138710031.91 20.434610041.9323.33856   10072 35.7792
10092.0537.3387410262.0638.1175910291.0437.22229 10412.139.5136610468.9339.33386
10525.6635.9375410538.46  36.46310554.0339.0359510608.9738.5091410637.17 35.9329
10665.37 36.259210721.7739.0140410738.4241.9486210764.0850.3006710792.1552.24926
#Mann= 3 , 0 , 0
9777.653    0.04       09777.653    0.04       010792.15    0.04       0
#XS Ineff= 2 , 0
       09949.878        10183.83       0
Bank Sta=9777.653,10792.15
Exp/Cntr=0.3,0.1

Type RM Length L Ch R = 3 ,5874.059,,,
BEGIN DESCRIPTION:
END DESCRIPTION:
Bridge Culvert--1,0,-1,-1, 0
Deck Dist Width WeirC Skew NumUp NumDn MinLoCord MaxHiCord MaxSubmerge Is_Ogee
18.198900,45.000000,2.6,0, 52, 52, , , 0.95, 0, 0,0,,
 9837.64 9853.10 9885.51 9896.32 9917.93 9939.54 9950.35 9959.48 9967.95 9987.34
 9987.3410037.3410037.3410061.1510072.9510103.7110120.6610152.7910223.2710245.04
10300.0410330.7410350.4710376.8210390.0010403.1810429.5410453.5710469.0710513.73
10550.5910557.5210564.3110578.0410586.7110591.7710605.5010619.2310630.5010632.95
10645.1010659.6910674.2910688.8910703.4810715.3210718.0810729.0510732.6810742.78
10747.2710769.06
   36.70   35.45   33.10   32.49   31.44   30.65   30.44   30.49   30.40   30.36
   30.36   30.26   30.26   30.21   30.25   30.76   30.85   31.25   31.73   31.80
   32.32   32.46   32.77   32.97   33.17   33.20   33.52   33.68   33.96   34.33
   34.81   35.09   35.18   35.30   35.19   35.28   35.93   35.98   36.16   36.30
   37.54   37.13   38.90   42.12   43.39   44.60   44.96   47.62   48.81   51.26
   52.03   54.10
 -963.30 -964.55 -966.90 -967.51 -968.56 -969.35 -969.56 -969.51 -969.60 -969.64
   27.36   27.26 -969.74 -969.79 -969.75 -969.24 -969.15 -968.75 -968.27 -968.20
 -967.68 -967.54 -967.23 -967.03 -966.83 -966.80 -966.48 -966.32 -966.04 -965.67
 -965.19 -964.91 -964.82 -964.70 -964.81 -964.72 -964.07 -964.02 -963.84 -963.70
 -962.46 -962.87 -961.10 -957.88 -956.61 -955.40 -955.04 -952.38 -951.19 -948.74
 -947.97 -945.90
 9837.64 9853.10 9885.51 9896.32 9917.93 9939.54 9950.35 9959.48 9967.95 9989.16
 9989.1610039.1610039.1610061.1510072.9510103.7110120.6610152.7910223.2710245.04
10300.0410330.7410350.4710376.8210390.0010403.1810429.5410453.5710469.0710513.73
10550.5910557.5210564.3110578.0410586.7110591.7710605.5010619.2310630.5010632.95
10645.1010659.6910674.2910688.8910703.4810715.3210718.0810729.0510732.6810742.78
10747.2710769.06
   36.70   35.45   33.10   32.49   31.44   30.65   30.44   30.49   30.40   30.35
   30.35   30.25   30.25   30.21   30.25   30.76   30.85   31.25   31.73   31.80
   32.32   32.46   32.77   32.97   33.17   33.20   33.52   33.68   33.96   34.33
   34.81   35.09   35.18   35.30   35.19   35.28   35.93   35.98   36.16   36.30
   37.54   37.13   38.90   42.12   43.39   44.60   44.96   47.62   48.81   51.26
   52.03   54.10
 -963.30 -964.55 -966.90 -967.51 -968.56 -969.35 -969.56 -969.51 -969.60 -969.65
   27.35   27.25 -969.75 -969.79 -969.75 -969.24 -969.15 -968.75 -968.27 -968.20
 -967.68 -967.54 -967.23 -967.03 -966.83 -966.80 -966.48 -966.32 -966.04 -965.67
 -965.19 -964.91 -964.82 -964.70 -964.81 -964.72 -964.07 -964.02 -963.84 -963.70
 -962.46 -962.87 -961.10 -957.88 -956.61 -955.40 -955.04 -952.38 -951.19 -948.74
 -947.97 -945.90
BR Coef=-1 , 0 , 0 ,, 0 ,,,0.8,0,1,0,
WSPro=,,,, 1 ,,,, 0 ,,,, 0 ,,,,-1 ,-1 ,-1 , 0 , 0 , 0 , 0 , 0
BC Design=,, 0 ,, 0 ,,,,,,

Type RM Length L Ch R = 1 ,5830.242,326.020900,326.020900,326.020900
XS GIS Cut Line= 6
834009.690581441852123.870515212834085.109732777851919.485908568
834047.315989852851853.714979336834053.205923855851742.787889794
834060.077513456851719.228153944834549.406280756851281.609959051
#Sta/Elev= 30
9653.76482.985279684.53781.701749695.19676.527499727.17355.297039755.75849.67191
9780.46942.571579842.41637.703969871.61930.777379956.203 30.19549966.217 27.6628
9976.23123.292319986.24514.766099996.25911.8783310006.2712.0409510016.2913.84765
10036.32  18.40110056.3424.9418910066.6726.49278 10083.126.9295110103.0324.21723
10134.7327.6672810156.4627.9860610179.9930.3805910195.0729.8213710626.0936.97769
10652.9838.9349810679.8743.7068710693.32  44.58610719.5452.1891810739.5754.25156
#Mann= 3 , 0 , 0
9653.764    0.04       09653.764    0.04       010739.57    0.04       0
#XS Ineff= 2 , 0
       0                10164.57       0
Bank Sta=9653.764,10739.57
Exp/Cntr=0.3,0.1

Type RM Length L Ch R = 1 ,5504.221,196.676500,196.676500,196.676500
XS GIS Cut Line= 6
834014.789931282852176.009161019834109.873895612 852102.50242523
834278.364315864    851986.03033834342.431088771 851939.38539928
 834407.05593036851888.442287441834654.701021075 851312.78763105
#Sta/Elev= 30
9666.08985.005129729.55382.510229754.833 62.30589767.47254.921439792.49851.51462
 9834.7549.988899841.07148.735249853.21441.127629877.50135.679739889.64427.83025
9901.78823.810189962.50420.355339992.8438.96571610009.837.74142410026.8316.43585
10036.4218.8287510077.4419.5199210086.3621.0831310109.7430.7269810221.7129.50555
10273.96 31.926810330.5730.30266 10461.236.02914 10476.434.7833610515.6336.55625
10559.1734.5783610635.38 35.115210722.47 42.649310744.2446.96754 10779.357.01725
#Mann= 3 , 0 , 0
9666.089    0.04       09666.089    0.04       0 10779.3    0.04       0
#XS Ineff= 2 , 0
       0                10154.75       0
Bank Sta=9666.089,10779.3
Exp/Cntr=0.3,0.1

Type RM Length L Ch R = 1 ,5307.544,192.152500,192.152500,192.152500
XS GIS Cut Line= 6
834124.177352799852258.389684082834259.933732194 852188.99340804
834502.094682338 852106.86674601834625.877887562852001.481750016
834881.482052564851846.144031589 835532.52371922851674.269031589
#Sta/Elev= 30
9727.181 83.03029751.49978.886949785.82163.413279841.47960.257139874.41751.48621
9906.35829.315659927.52121.594659948.55318.529229969.3517.677694 10052.57.062141
10084.4413.6698310116.9715.3007710151.0522.0026410187.6121.0028610210.1128.26852
10226.2829.5925610283.3827.7295310555.9332.1448110567.6330.0606310633.2829.82417
10653.9733.2210610912.5341.8825710922.8844.4905711067.6745.4205211078.0248.24966
 11098.764.0075311119.3967.0596411150.4177.02996 11171.179.8963811271.9681.55193
#Mann= 3 , 0 , 0
9727.181    0.04       09727.181    0.04       011271.96    0.04       0
#XS Ineff= 2 , 0
       0                               0
Bank Sta=9727.181,11271.96
Exp/Cntr=0.3,0.1

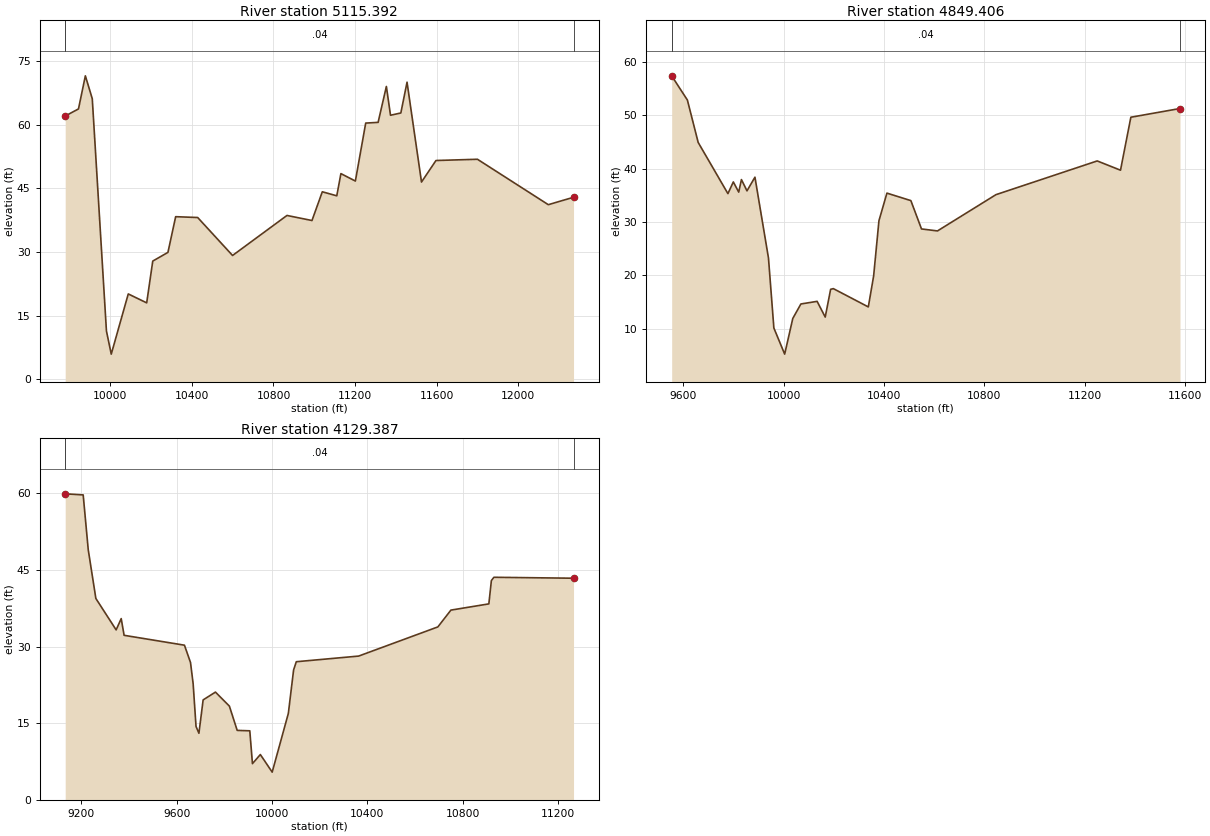
Type RM Length L Ch R = 1 ,5115.392,265.986400,265.986400,265.986400
XS GIS Cut Line= 6
  834236.2582059852436.279744287834573.868729244852239.792426941
834866.435412861852026.930259648835079.997194962851929.034324758
836140.898263372851736.533397258 836555.57833115851646.830328829
#Sta/Elev= 30
9779.15362.09152 9844.2563.774789877.93671.584889911.82366.18798 9981.3111.35062
10004.915.90455810088.2720.1114410178.6218.0042510208.33 27.861910282.7329.91465
10320.5938.3418410428.5738.1441710599.4629.1841210866.2138.6319410988.7437.43622
11039.4444.2181811110.3443.26424 11130.648.50629 11201.5  46.75111252.1560.43387
11312.9260.5973111353.4369.0766511373.6962.2794511424.3362.8166311454.7270.08465
11525.6246.5168511596.5451.5987511799.8651.8923112147.1741.1751112270.8242.92531
#Mann= 3 , 0 , 0
9779.153    0.04       09779.153    0.04       012270.82    0.04       0
#XS Ineff= 2 , 0
       0                               0
Bank Sta=9779.153,12270.82
Exp/Cntr=0.3,0.1

Type RM Length L Ch R = 1 ,4849.406,720.018600,720.018600,720.018600
XS GIS Cut Line= 4
834482.826021075 852883.10013105834730.221854448852268.516797721
835370.846854419852041.954297706836034.909354448851872.683464378
#Sta/Elev= 30
9552.95357.404229615.58452.869989658.703 44.91079777.28135.31629 9798.8437.51173
  9820.435.59541 9831.1837.949219853.34735.836539885.07938.401649938.97823.25582
9960.53710.1183810003.665.220953   1003611.9091710068.3414.6238210133.0115.11678
10165.3512.1691310186.9117.3720410197.6917.5031410337.2114.0727410358.4219.86083
10379.6330.2383110411.4535.4118310506.92  34.00510549.3428.6933710612.9928.31999
10846.3435.1230111250.1341.44455   1134339.7080111384.2849.6391111580.2751.27611
#Mann= 3 , 0 , 0
9552.953    0.04       09552.953    0.04       011580.27    0.04       0
#XS Ineff= 2 , 0
       0                               0
Bank Sta=9552.953,11580.27
Exp/Cntr=0.3,0.1

Type RM Length L Ch R = 1 ,4129.387,0.000000,0.000000,0.000000
XS GIS Cut Line= 6
834524.076135576852959.101007447834909.235112833852819.649691684
835041.757771932852629.966736825 835141.76887587852548.586099284
835773.642461198852237.535608106 836393.39113461852023.960711285
#Sta/Elev= 30
 9132.7259.879969208.14959.66554 9229.4248.917579261.32539.402859346.40833.25548
9367.67835.465299379.75932.19529 9632.9630.260759658.36626.874489669.37522.73674
9681.51414.356229693.64913.02857 9711.2919.554549762.994 21.08289821.434 18.3378
9854.20713.588619907.06613.50457 9918.177.0830139951.2998.864776   100015.422482
10068.7616.9094710090.8525.4322410102.1727.0267310363.5728.1295610695.9633.83695
10750.7637.1259410909.8738.3449110920.4542.9020310931.0343.5482511265.08 43.3667
#Mann= 3 , 0 , 0
 9132.72    0.04       0 9132.72    0.04       011265.08    0.04       0
#XS Ineff= 2 , 0
       0                               0
Bank Sta=9132.72,11265.08
Exp/Cntr=0.3,0.1